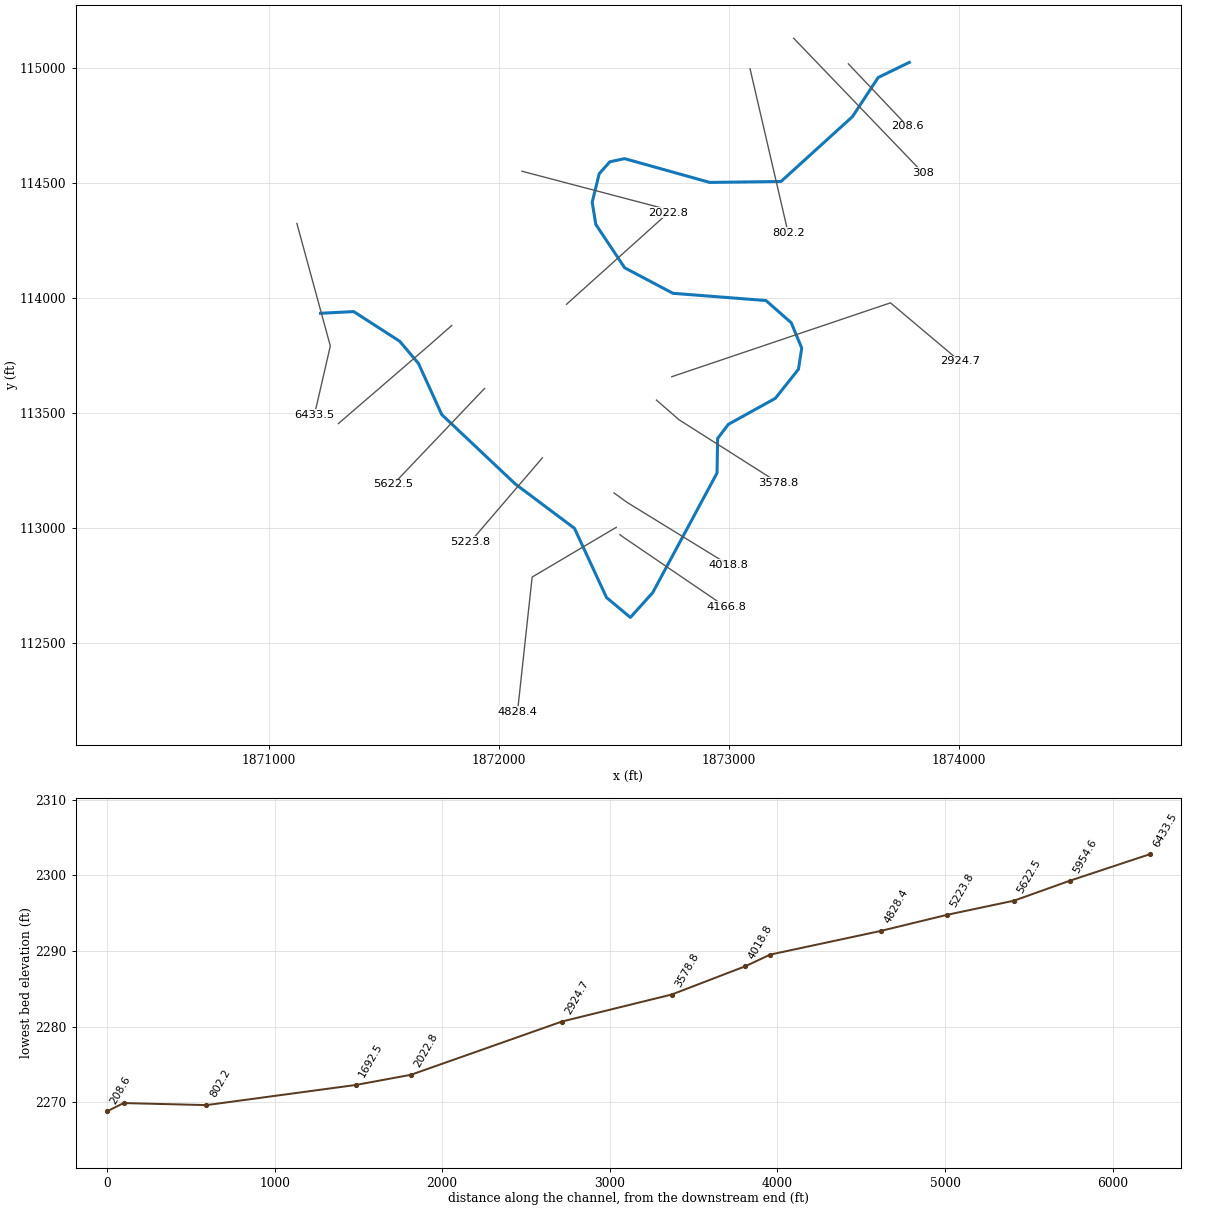
--- LrlFrk.prj (project) ---

Proj Title=LrlFrk
Current Plan=p01
Default Exp/Contr=0,0
English Units
Geom File=g01
Flow File=f01
Plan File=p01
BEGIN DESCRIPTION:
END DESCRIPTION:
DSS File=dss
DSS Export Rating Curves= 0
DSS Export Rating Curve Sorted= 0
DSS Export Volume Flow Curves= 0
DXF OffsetX= 0
DXF OffsetY= 0
DXF ScaleX= 0
DXF ScaleY= 0

--- LrlFrk.p01 (plan) ---

Plan Title=Floodplain
Program Version=4.10
Short Identifier=Floodplain
Geom File=g01
Flow File=f01
Subcritical Flow
K Sum by GR= 0
Std Step Tol= 0.01
Critical Tol= 0.01
Num of Std Step Trials= 20
Max Error Tol= 0.3
Flow Tol Ratio= 0.001
Split Flow NTrial= 30
Split Flow Tol= 0.02
Split Flow Ratio= 0.02
Log Output Level= 0
Friction Slope Method= 1
Unsteady Friction Slope Method= 2
Unsteady Bridges Friction Slope Method= 1
Parabolic Critical Depth
Global Vel Dist= 0 , 0 , 0
Global Log Level= 0
CheckData=True
Encroach Param=-1 ,0,0, 0
Run HTab= 0
Run UNet= 0
Run PostProcess= 0
Run WQNet= 0
UNET Theta= 0
UNET Theta Warmup= 0
UNET ZTol= 0
UNET ZSATol= 0
UNET MxIter= 0
UNET MaxInSteps= 0
UNET DtIC= 0
UNET DtMin= 0
UNET MaxCRTS= 0
UNET WFStab= 0
UNET SFStab= 0
UNET WFX= 1
UNET SFX= 1
UNET DSS MLevel= 1
UNET DZMax Abort= 0
UNET Convert EG Bridges= 0
UNET Use Existing IB Tables= 0
UNET Froude Reduction=False
UNET Froude Limit= 0
UNET Froude Power= 0
UNET Time Slicing=0,0, 5
UNET Junction Losses=0
DSS File=dss
Write IC File= 0
Write IC File at Sim End=0
Echo Input=False
Echo Parameters=False
Echo Output=False
Write Detailed= 0
WQ AD Non Conservative
WQ ULTIMATE=-1
WQ Max Comp Step=1HOUR
WQ Output Interval=15MIN
WQ Output Selected Increments= 0
WQ Output face flow=0
WQ Output face velocity=0
WQ Output face area=0
WQ Output face dispersion=0
WQ Output cell volume=0
WQ Output cell surface area=0
WQ Output cell continuity=0
WQ Output cumulative cell continuity=0
WQ Output face conc=0
WQ Output face dconc_dx=0
WQ Output face courant=0
WQ Output face peclet=0
WQ Output face adv mass=0
WQ Output face disp mass=0
WQ Output cell mass=0
WQ Output cell source sink temp=0
WQ Output cell source sink nsm=0
WQ Output MaxMinRange=-1
WQ Daily Max Min Mean=-1
WQ Daily Range=0
WQ Daily Time=0
WQ Create Restart=0
WQ Fixed Restart=0
WQ System Summary=0
WQ Use Fixed Temperature=0
Sorting and Armoring Iterations= 10
XS Update Threshold= 0.02
Hydraulics Update Threshold= 0.02
Energy Slope Method= 1
Volume Change Method= 0
XS Weighting Method= 0
Number of US Weighted Cross Sections= 1
Number of DS Weighted Cross Sections= 1
Upstream XS Weight=0.25
Main XS Weight=0.5
Downstream XS Weight=0.25
Number of DS XS's Weighted with US Boundary= 1
Upstream Boundary Weight= 1
Weight of XSs Associated with US Boundary= 0
Number of US XS's Weighted with DS Boundary= 1
Downstream Boundary Weight= 0.5
Weight of XSs Associated with DS Boundary= 0.5
Sediment Output Level= 4
Mass or Volume Output= 0
Output Increment Type= 1
Profile and TS Output Increment= 10
XS Output Flag= 0
XS Output Increment= 10
Disregard all LS=0
Disregard all Conn=0
Disregard all Breaches=0
Disregard all Pumps=0

--- LrlFrk.f01 (steady flow) ---

Flow Title=NFF Regression Equation
Program Version=4.00
Number of Profiles=1
Profile Names=P100yr
River Rch & RM=LrlFrk,Main      ,6433.5
2572.595
River Rch & RM=LrlFrk,Main      ,308
2636.110
Boundary for River Rch & Prof#=LrlFrk,Main      ,1
Up Type=0
Dn Type=3
Dn Slope=0.015923

--- LrlFrk.g01 (geometry) ---

Geom Title=USGS 3m DEM
Program Version=4.10

River Reach=LrlFrk          ,Main
Reach XY= 30
     1871226.096      113933.008     1871369.938       113940.45
     1871569.597       113811.75      1871651.27      113715.398
     1871752.599      113492.984      1872071.71      113191.793
     1872329.184      112998.779     1872468.229      112698.212
     1872571.992      112611.833     1872669.131       112719.96
     1872948.312      113239.264     1872950.771      113388.888
     1872997.256      113450.429     1873201.683       113563.71
     1873301.924      113689.854     1873316.249      113781.857
     1873270.587       113892.06     1873160.871      113988.458
     1872756.803      114019.822     1872547.051      114130.586
     1872421.671      114319.096     1872405.998      114415.211
     1872436.416      114539.127     1872482.612      114591.034
     1872546.684      114604.837     1872916.518      114501.516
      1873226.03      114505.449     1873536.527      114787.204
     1873648.345      114957.281     1873783.369      115022.933

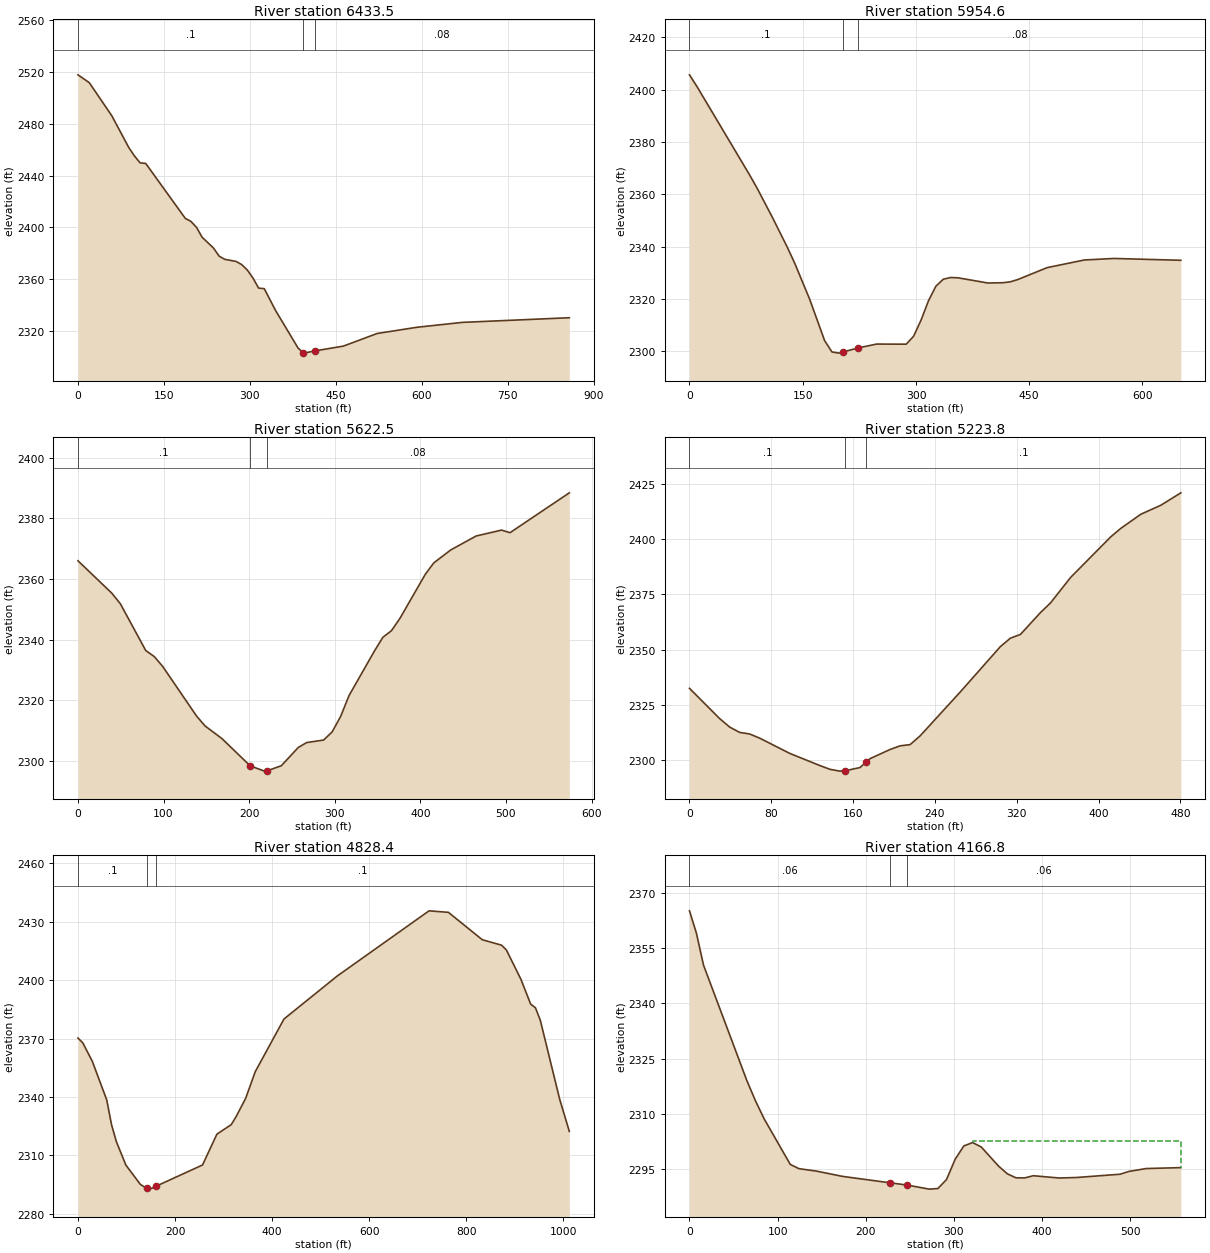
Type RM Length L Ch R = 1 ,6433.5  ,507,478.7,450.5
XS GIS Cut Line= 3
     1871123.294      114323.188     1871268.476      113790.995
     1871199.798      113493.023
#Sta/Elev= 30
       0 2517.96    19.7  2511.9    59.1 2486.25    88.7 2461.72    98.5 2455.28
   108.4  2449.9   118.2 2449.46   187.2 2407.03     197 2404.67   206.9 2400.01
   216.7 2392.36   236.4 2384.09   246.3  2377.8   256.1 2375.32   275.8 2373.72
   285.7 2371.26   295.5 2367.04   305.4 2360.83   315.2 2353.08   325.1 2352.63
   344.8 2335.77   384.2 2306.64   393.4 2303.04     394 2302.81   413.4 2304.53
     463 2308.22   522.1 2317.99   591.1 2322.77     670 2326.56   857.4 2330.17
#Mann= 3 , 0 , 0
       0      .1       0   393.4    .045       0   413.4     .08       0
Bank Sta=393.4,413.4
XS Rating Curve= 0 ,0
Exp/Cntr=0.3,0.1

Type RM Length L Ch R = 1 ,5954.6  ,329.4,331.9,334.4
XS GIS Cut Line= 3
     1871795.772      113879.936     1871690.948      113787.818
     1871303.695      113454.067
#Sta/Elev= 30
       0 2405.68      10 2401.16    79.7 2367.38    89.7 2362.27   109.6 2351.31
   129.6 2339.76   139.6 2333.52   159.2 2319.88   178.9 2304.12   188.7 2299.73
   198.5 2299.29   203.2 2299.71   223.2 2301.26   247.7 2302.75     287 2302.71
   296.8 2305.73   306.7  2311.9   316.5 2319.27   326.3 2324.85   336.2 2327.56
     346  2328.2   355.8 2328.08   395.2  2326.1   414.8  2326.2   424.7 2326.53
   434.5 2327.38   473.8 2331.98     523  2334.9   562.3 2335.48   650.8 2334.78
#Mann= 3 , 0 , 0
       0      .1       0   203.2    .045       0   223.2     .08       0
Bank Sta=203.2,223.2
XS Rating Curve= 0 ,0
Exp/Cntr=0.3,0.1

Type RM Length L Ch R = 1 ,5622.5  ,397.3,398.6,399.9
XS GIS Cut Line= 2
     1871938.714      113606.759     1871542.782      113191.045
#Sta/Elev= 30
       0 2366.03    39.6 2355.33    49.5 2351.86    79.2 2336.43    89.1 2334.45
      99 2331.18   138.6  2314.8   148.5 2311.56   168.3 2307.37   201.1 2298.43
   217.8 2296.66   221.1 2296.78   237.6 2298.44   257.4 2304.46   267.2 2306.08
     287 2306.91   296.9 2309.58   306.8 2314.64   316.7 2321.57   346.4 2336.28
   356.3 2340.82   366.2 2342.95   376.1    2347   405.8 2361.57   415.7 2365.33
   435.5  2369.6   465.2  2374.2   494.9 2376.15   504.8 2375.29   574.1 2388.44
#Mann= 3 , 0 , 0
       0      .1       0   201.1    .045       0   221.1     .08       0
Bank Sta=201.1,221.1
XS Rating Curve= 0 ,0
Exp/Cntr=0.3,0.1

Type RM Length L Ch R = 1 ,5223.8  ,403.6,395.3,387.1
XS GIS Cut Line= 2
     1872189.656      113304.993     1871876.921      112940.272
#Sta/Elev= 30
       0 2332.39    29.4 2318.69    39.2 2314.83      49 2312.37    58.8 2311.66
    68.6 2309.77      98 2302.85   127.5 2297.32   137.3 2295.62   147.1 2294.79
   152.5 2294.97   166.7 2296.42   172.5 2298.81   176.5 2300.45   196.1 2304.62
   205.9 2306.27   215.7 2306.83   225.5 2310.81   264.7 2330.72     304 2351.36
   313.8 2355.17   323.6 2356.88   343.2 2366.82     353 2371.19   372.6 2382.74
   411.8 2401.15   421.6 2404.99   441.2 2411.42   460.8 2415.52   480.4 2421.17
#Mann= 3 , 0 , 0
       0      .1       0   152.5    .045       0   172.5      .1       0
Bank Sta=152.5,172.5
XS Rating Curve= 0 ,0
Exp/Cntr=0.3,0.1

Type RM Length L Ch R = 1 ,4828.4  ,609.3,661.1,712.2
XS GIS Cut Line= 3
     1872510.481      113003.227     1872145.186      112787.226
     1872081.656      112202.753
#Sta/Elev= 30
       0 2370.25     9.9 2367.78    29.6 2358.25    59.2  2338.5    69.1  2325.8
      79  2317.1    98.7    2305   128.3 2295.15   141.5    2293     148 2292.66
   161.5 2294.22   256.6 2305.06   286.2 2320.88   315.8 2325.78   325.7 2329.84
   345.4 2339.24   365.2 2352.96   424.4 2380.01     534 2402.06   723.3 2435.56
   763.2 2434.78   832.9 2420.73   872.8 2417.91   882.8 2415.38   912.6 2400.39
   932.6 2387.69   942.5 2385.76   952.5 2379.38   992.4 2338.84  1012.3  2322.3
#Mann= 3 , 0 , 0
       0      .1       0   141.5    .045       0   161.5      .1       0
Bank Sta=141.5,161.5
XS Rating Curve= 0 ,0
Exp/Cntr=0.3,0.1

Type RM Length L Ch R = 1 ,4166.8  ,146.8,148,149.2
XS GIS Cut Line= 3
     1872526.364      112971.462      1872539.07      112961.932
     1872986.954       112656.99
#Sta/Elev= 30
       0 2365.11     7.9    2359    15.9 2350.37    65.1 2319.01      75 2313.45
    84.8 2308.58   114.4 2296.23   124.2 2295.08     144 2294.42   173.5 2292.99
   227.2 2291.25   247.2 2290.62     272 2289.52   281.9 2289.68   291.7 2292.12
   301.6 2297.66   311.4 2301.25   321.3 2302.17   331.1 2300.98   350.8 2295.77
   360.7 2293.69   370.5  2292.6   380.4 2292.56   390.2 2293.16   419.8 2292.54
   439.5 2292.68   488.8 2293.57   498.6 2294.32   518.3 2295.11   557.7 2295.36
#Mann= 3 , 0 , 0
       0     .06       0   227.2    .045       0   247.2     .06       0
#XS Ineff= 2 , 0
                          321.53         2302.51
Permanent Ineff=
       F       F
Bank Sta=227.2,247.2
XS Rating Curve= 0 ,0
Exp/Cntr=0.3,0.1

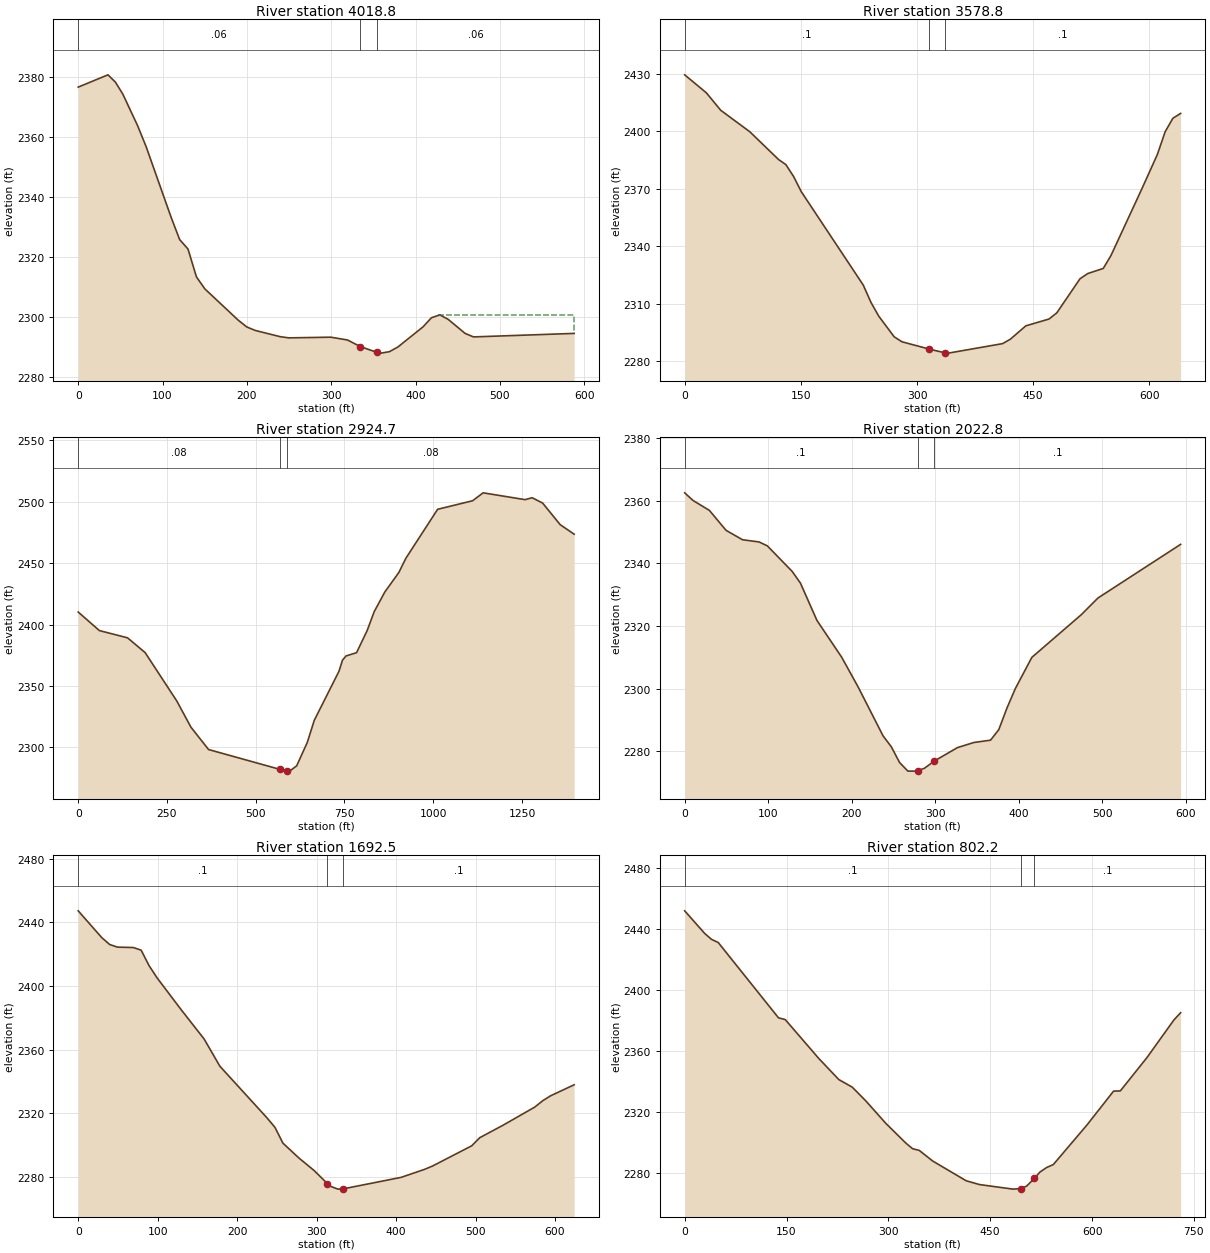
Type RM Length L Ch R = 1 ,4018.8  ,441.4,439.5,437
XS GIS Cut Line= 3
     1872500.952      113152.521     1872558.129      113111.227
     1872999.182      112840.356
#Sta/Elev= 30
       0 2376.75    35.3 2380.85    44.1 2378.42    52.9 2374.42    70.5 2363.84
    80.5 2356.91   110.3 2333.21   120.3 2325.87   130.2 2322.72   140.2 2313.42
   150.2 2309.41     190 2298.92   199.9 2296.71   209.9 2295.55   239.7 2293.46
   249.7 2293.07   299.5  2293.3   319.4 2292.36   334.5 2290.16   354.5 2288.22
   359.2 2287.98   369.1 2288.47   379.1 2290.03     409 2296.77   418.9 2299.79
   428.9 2300.74   438.8 2299.23   458.7 2294.58   468.7 2293.39   588.1 2294.56
#Mann= 3 , 0 , 0
       0     .06       0   334.5    .045       0   354.5     .06       0
#XS Ineff= 2 , 0
                          426.87         2300.71
Permanent Ineff=
       F       F
Bank Sta=334.5,354.5
XS Rating Curve= 0 ,0
Exp/Cntr=0.3,0.1

Type RM Length L Ch R = 1 ,3578.8  ,630.6,654.3,678.6
XS GIS Cut Line= 3
     1872685.188      113555.935     1872783.659       113470.17
     1873214.158      113197.019
#Sta/Elev= 30
       0 2429.45      28 2420.06    46.6 2410.93      84 2399.79   121.3 2385.23
   130.6 2382.64   140.6 2376.45   150.6 2368.46   230.6 2319.75   240.6 2310.67
   250.6 2303.53   270.5 2292.77   280.5 2290.17     316 2286.33     336 2284.39
   340.5 2284.24   410.5  2289.2   420.5 2291.49   440.5 2298.47   470.5 2302.04
   480.5 2305.24   510.5 2323.05   520.5 2325.76   540.5 2328.42   550.5 2335.19
   590.4    2370   610.4 2387.91   620.4 2399.73   630.4 2406.78   640.4 2409.32
#Mann= 3 , 0 , 0
       0      .1       0     316    .045       0     336      .1       0
Bank Sta=316,336
XS Rating Curve= 0 ,0
Exp/Cntr=0.3,0.1

Type RM Length L Ch R = 1 ,2924.7  ,890.9,901.3,911.7
XS GIS Cut Line= 3
     1872751.894      113657.582     1873701.663      113978.407
     1874003.429      113724.289
#Sta/Elev= 30
       0  2410.2    59.6 2395.11     139  2389.2   188.6 2377.15   277.9 2337.66
   317.6 2316.43   367.2 2298.25   568.6 2282.07   588.6 2280.73   595.5 2280.67
   615.4 2284.98   645.2 2303.99     665 2322.05   734.5 2361.94   744.4 2370.99
   754.4 2374.44   784.1 2377.12   813.9  2395.1   833.8 2410.53   863.5 2426.42
   903.2 2442.42   923.1 2454.03  1012.4 2493.84    1111 2500.81  1140.6 2507.26
  1258.9  2501.7  1278.6 2503.26  1308.2 2498.94  1357.6 2481.36    1397 2473.59
#Mann= 3 , 0 , 0
       0     .08       0   568.6    .045       0   588.6     .08       0
Bank Sta=568.6,588.6
XS Rating Curve= 0 ,0
Exp/Cntr=0.3,0.1

Type RM Length L Ch R = 1 ,2022.8  ,355,330.2,305.4
XS GIS Cut Line= 2
      1872294.48      113972.054     1872736.012      114369.115
#Sta/Elev= 30
       0 2362.56     9.9 2360.14    29.7 2356.92    49.5 2350.58    69.3 2347.56
    89.1 2346.86      99  2345.6   128.7 2337.45   138.6 2333.71   158.4 2321.77
     188 2310.02   207.8 2300.46   237.5  2284.9   247.4 2281.41   257.3 2276.38
   267.2 2273.63   277.1 2273.62     279 2273.79     287 2274.52     299 2276.86
   326.6 2281.14   346.4 2282.78   366.2 2283.51   376.1 2286.88     386 2293.86
   395.9    2300   415.7 2309.98     475 2323.64   494.8 2328.94   593.8 2346.09
#Mann= 3 , 0 , 0
       0      .1       0     279    .045       0     299      .1       0
Bank Sta=279,299
XS Rating Curve= 0 ,0
Exp/Cntr=0.3,0.1

Type RM Length L Ch R = 1 ,1692.5  ,917.3,889.7,862.1
XS GIS Cut Line= 2
     1872100.715      114550.174     1872704.247       114391.35
#Sta/Elev= 30
       0 2447.22    29.7 2430.35    39.6 2426.04    49.5 2424.39    69.3 2424.16
    79.2 2422.49    89.2 2412.74    99.1 2405.19   128.8 2385.56   158.5 2366.61
   178.3 2349.52   237.7    2317   247.6  2311.1   257.6 2301.18   277.4 2291.99
   297.2 2283.82   313.5 2275.78     317 2274.15   326.9 2272.27   333.5 2272.45
   406.2 2279.64   435.9 2284.71   445.8 2286.77   495.3 2299.53   505.2 2304.57
   534.9 2312.52   574.6 2323.87   584.5 2327.82   594.4 2330.92   624.1 2337.87
#Mann= 3 , 0 , 0
       0      .1       0   313.5    .045       0   333.5      .1       0
Bank Sta=313.5,333.5
XS Rating Curve= 0 ,0
Exp/Cntr=0.3,0.1

Type RM Length L Ch R = 1 ,802.2   ,480.2,494,507.9
XS GIS Cut Line= 2
     1873091.778      114994.882     1873256.955       114283.35
#Sta/Elev= 30
       0 2451.68    29.6 2436.83    39.5 2433.02    49.4 2430.96   138.2 2381.66
   148.1 2380.54   197.4 2355.15     227 2341.29   246.8 2336.32   266.5 2327.47
   296.1 2312.71   325.7 2299.75   335.6 2296.07   345.5 2294.95   365.2 2288.02
   414.6 2275.08   434.3 2272.59   483.7 2269.61   495.1 2269.99   503.4 2271.51
   515.1 2276.65   523.2 2280.77     533 2283.73   542.9 2285.67   592.3 2311.48
   631.7 2333.74   641.6 2333.86   681.1 2355.83   720.6 2380.33   730.4 2385.01
#Mann= 3 , 0 , 0
       0      .1       0   495.1    .045       0   515.1      .1       0
Bank Sta=495.1,515.1
XS Rating Curve= 0 ,0
Exp/Cntr=0.3,0.1

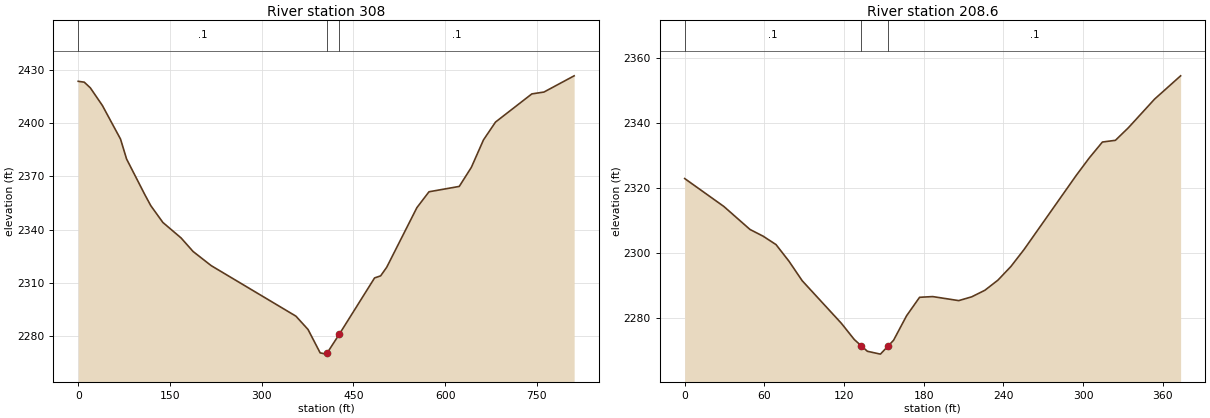
Type RM Length L Ch R = 1 ,308     ,100,99.5,99
XS GIS Cut Line= 2
     1873281.159      115127.733     1873843.089      114542.782
#Sta/Elev= 30
       0 2423.54     9.9 2423.05    19.8 2419.87    39.6 2409.88    69.2 2391.01
    79.1 2379.79   108.8 2359.81   118.7  2353.5   138.5 2344.03   168.2 2335.33
   187.9 2327.68   217.6  2319.7   356.1 2291.26   375.9 2283.75   395.7 2270.59
   405.6 2269.88     407 2270.45     427 2281.09   484.7 2312.79   494.6 2313.97
   504.5 2318.78   553.9 2352.38   573.7 2361.32   623.2 2364.34     643  2375.1
   662.8 2390.54   682.5 2400.59   741.9 2416.45   761.7 2417.49   811.1 2426.63
#Mann= 3 , 0 , 0
       0      .1       0     407    .045       0     427      .1       0
Bank Sta=407,427
XS Rating Curve= 0 ,0
Exp/Cntr=0.3,0.1

Type RM Length L Ch R = 1 ,208.6   ,216,207.8,199.6
XS GIS Cut Line= 2
     1873518.783       115016.44     1873775.881      114745.474
#Sta/Elev= 30
       0 2322.88    29.5 2314.28    49.2 2307.19      59 2305.14    68.8 2302.53
    78.6 2297.38    88.5  2291.4     118 2278.28   127.8 2273.25   133.1 2271.31
   137.6 2269.66   147.4 2268.78   153.1 2271.23   157.3 2273.04   167.1 2280.59
   176.9 2286.29   186.8 2286.51   206.4 2285.27   216.2 2286.44   226.1 2288.46
   235.9 2291.57   245.7 2295.79   255.6 2301.02   294.9 2323.86   304.7 2329.23
   314.6 2334.13   324.4 2334.66   334.2 2338.55   353.9 2347.36   373.5 2354.53
#Mann= 3 , 0 , 0
       0      .1       0   133.1    .045       0   153.1      .1       0
Bank Sta=133.1,153.1
XS Rating Curve= 0 ,0
Exp/Cntr=0.3,0.1

Chan Stop Cuts=-1
Use User Specified Reach Order=0
Composite Channel Slope=5